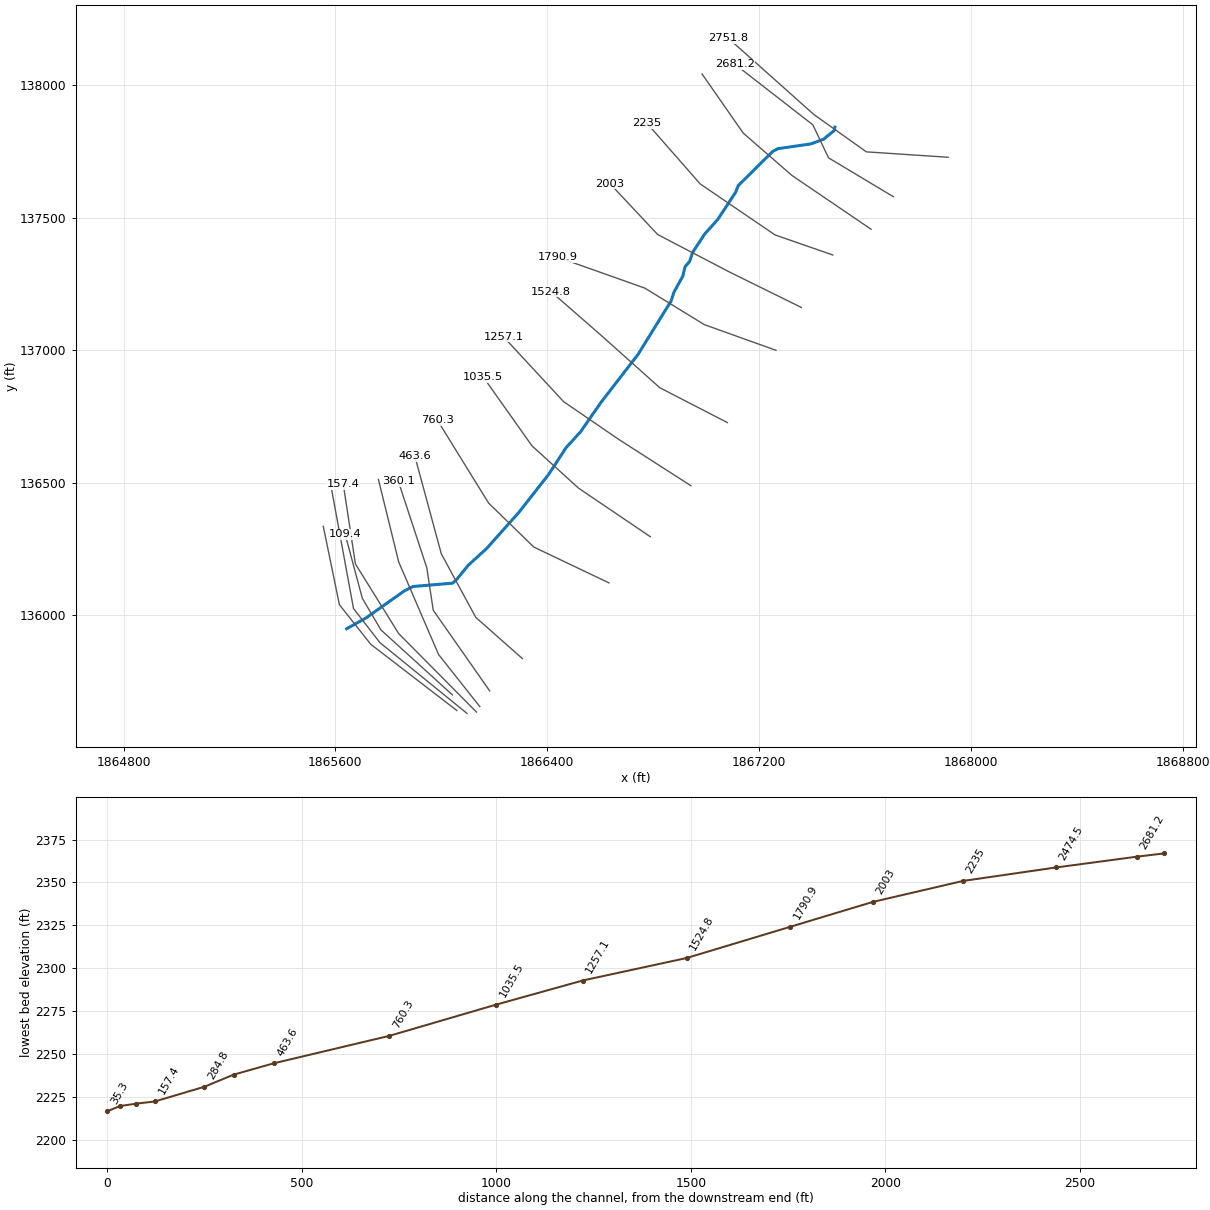
--- Little Fork Trib 1.prj (project) ---

Proj Title=Little Fork Trib 1
Current Plan=p01
Default Exp/Contr=0,0
English Units
Geom File=g01
Flow File=f01
Plan File=p01
BEGIN DESCRIPTION:
END DESCRIPTION:
DSS Export Rating Curves= 0
DSS Export Rating Curve Sorted= 0
DSS Export Volume Flow Curves= 0
DXF OffsetX= 0
DXF OffsetY= 0
DXF ScaleX= 0
DXF ScaleY= 0

--- Little Fork Trib 1.p01 (plan) ---

Plan Title=Floodplain
Program Version=4.00
Geom File=g01
Flow File=f01
K Sum by GR=0
Std Step Tol=0.01
Critical Tol=0.01
Num of Std Step Trials=20
Max Error Tol=0.3
Flow Tol Ratio=0.001
Split Flow NTrial=30
Split Flow Tol=0.02
Split Flow Ratio=0.02
Log Output Level=0
Friction Slope Method=1
Unsteady Friction Slope Method=2
Unsteady Bridges Friction Slope Method=1
Global Log Level=0
CheckData=False
Run HTab=0
Run UNet=0
Run PostProcess=0
UNET Theta=0
UNET Theta Warmup=0
UNET ZTol=0
UNET ZSATol=0
UNET MxIter=0
UNET MaxInSteps=0
UNET DtIC=0
UNET DtMin=0
UNET MaxCRTS=0
UNET WFStab=0
UNET SFStab=0
UNET WFX=0
UNET SFX=0
UNET DSS MLevel=0
UNET DZMax Abort=0
UNET Convert EG Bridges=0
UNET Use Existing IB Tables=0
UNET Froude Limit=0
UNET Froude Power=0
Write IC File=0
Echo Input=False
Echo Output=False
Write Detailed=0

--- Little Fork Trib 1.f01 (steady flow) ---

Flow Title=NFF Regression Equation
Program Version=4.00
Number of Profiles=1
Profile Names=P100yr
River Rch & RM=Little Fork T...,Main      ,2751.8
534.8230
River Rch & RM=Little Fork T...,Main      ,2681.2
564.4841
River Rch & RM=Little Fork T...,Main      ,284.8
618.3173
Boundary for River Rch & Prof#=Little Fork T...,Main      ,1
Up Type=0
Dn Type=3
Dn Slope=0.034842

--- Little Fork Trib 1.g01 (geometry) ---

Geom Title=USGS 10m DEM
Program Version=4.00

River Reach=Little Fork T...,Main
Reach XY= 30
     1867486.215      137841.982     1867483.473      137829.303
     1867443.568      137796.428      1867394.62      137778.629
     1867270.439      137760.704     1867250.974      137749.965
     1867121.438       137621.77      1867111.37      137596.266
     1867044.253      137494.247     1866993.915      137437.868
     1866948.758      137368.843     1866937.693      137335.648
     1866919.989      137314.255     1866911.875      137279.585
     1866877.801      137217.723     1866867.615      137185.901
     1866742.895      136984.154     1866603.962      136804.279
     1866525.434      136691.522     1866471.069      136631.787
     1866405.099      136530.854     1866292.973      136387.747
     1866171.259      136251.279     1866101.923       136188.14
     1866058.288      136134.579     1866042.859      136120.351
     1865893.187      136107.599     1865860.971      136091.491
     1865716.668      135989.473     1865642.611       135948.15

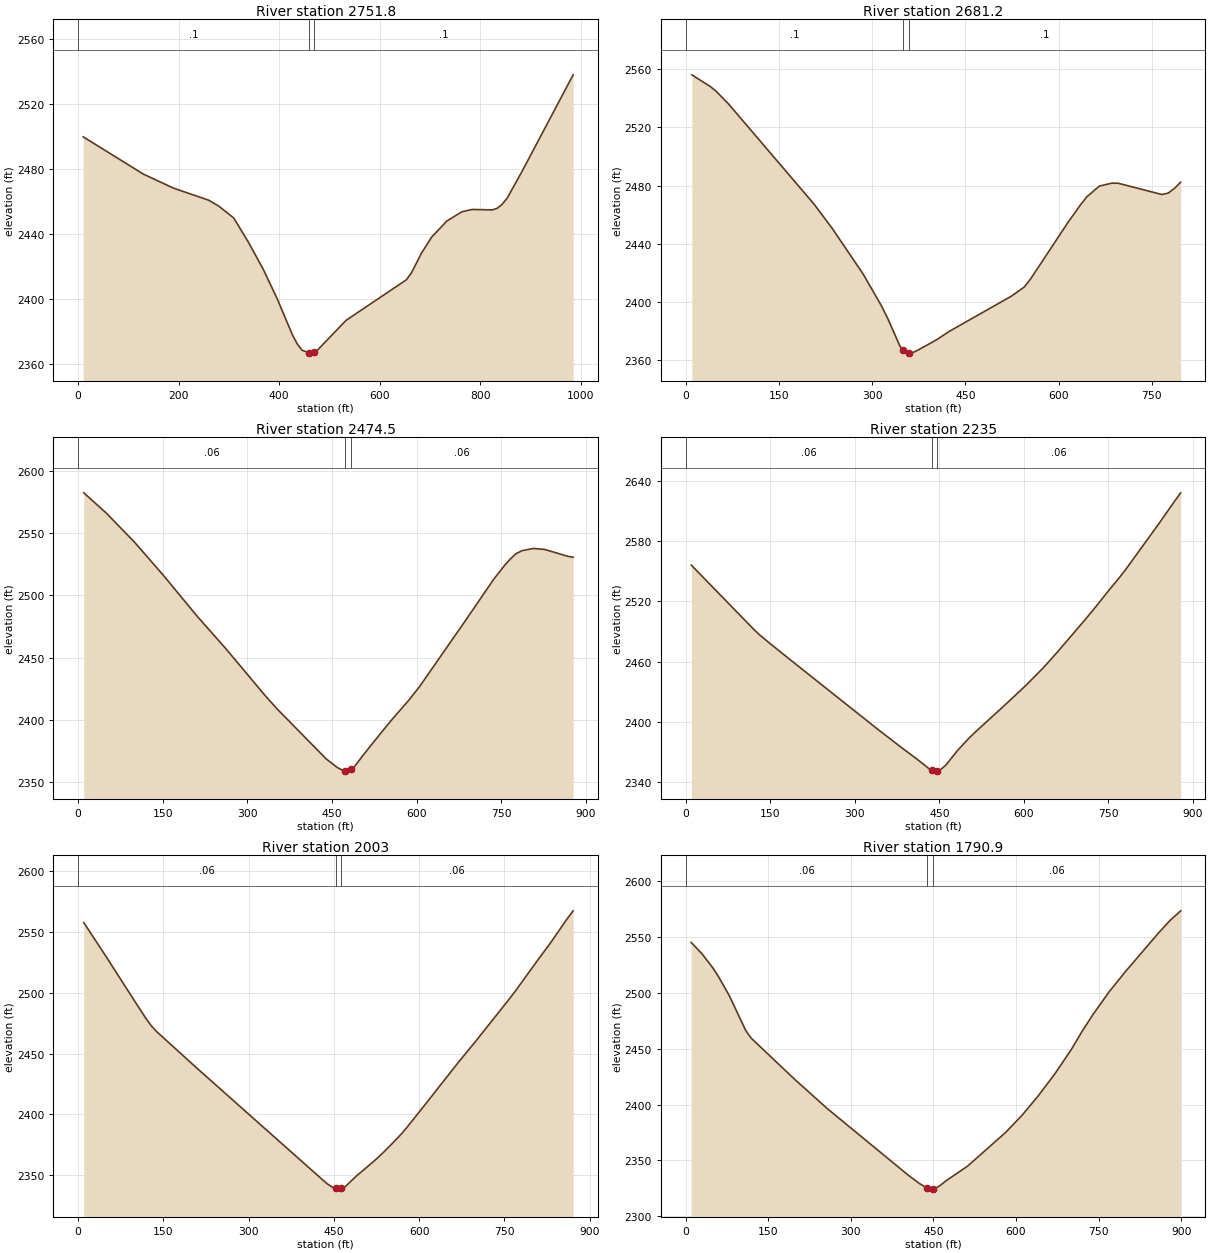
Type RM Length L Ch R = 1 ,2751.8  ,81,70.6,60.1
XS GIS Cut Line= 4
     1867913.646      137728.288     1867604.815      137748.717
     1867406.717      137889.632     1867083.913      138177.345
#Sta/Elev= 30
      10 2499.98   129.8 2477.04   189.7 2468.42   259.6 2461.02   279.6 2457.42
   309.5 2450.09   338.7 2435.21   367.9 2418.78     397 2399.74   426.2 2378.27
   435.9 2372.63   445.6 2368.68   460.1 2367.08   465.1 2366.93   470.1 2367.65
   474.8 2368.33   533.2 2387.11   653.2 2412.06   663.2  2416.3   683.3 2428.48
   703.5  2438.3   733.6 2448.18   763.8 2453.92   783.9  2455.3   824.1 2455.04
   834.2 2456.05   844.2 2458.62   854.3 2462.54   884.5  2479.4     985 2538.12
#Mann= 3 , 0 , 0
       0      .1       0   460.1    .045       0   470.1      .1       0
Bank Sta=460.1,470.1
XS Rating Curve= 0 ,0
Exp/Cntr=0.3,0.1

Type RM Length L Ch R = 1 ,2681.2  ,198.3,206.7,215.1
XS GIS Cut Line= 4
     1867706.927      137579.211     1867461.858      137726.252
     1867402.633      137850.829     1867108.549      138079.561
#Sta/Elev= 30
     9.9 2556.17    39.4 2548.19    49.3 2544.77      69 2536.13     207  2467.1
   236.5 2450.24   285.8 2419.11   315.4 2397.12   325.2 2388.68   344.9 2369.66
   349.8 2367.35   354.8    2365   359.8 2365.11   364.6 2365.22   374.5 2367.25
     404 2374.27   423.7 2379.86   524.4 2404.24   544.6 2410.41   554.6 2415.79
   615.1 2454.83   635.2  2466.9   645.3 2472.34   665.4 2479.74   685.5 2481.75
   695.6 2481.71   766.1 2473.96   776.2 2474.92   786.2  2478.1   796.3 2482.44
#Mann= 3 , 0 , 0
       0      .1       0   349.8    .045       0   359.8      .1       0
Bank Sta=349.8,359.8
XS Rating Curve= 0 ,0
Exp/Cntr=0.3,0.1

Type RM Length L Ch R = 1 ,2474.5  ,237,239.5,242
XS GIS Cut Line= 4
     1867622.573        137456.5     1867323.416      137659.927
     1867139.933      137819.478     1866984.371      138042.848
#Sta/Elev= 30
      10 2582.24    50.2 2565.83   100.5 2542.31   150.7 2516.15     211 2483.07
   261.3 2457.31   331.6 2419.29   351.7 2409.12   439.6 2368.54     459 2361.72
   468.8 2359.39   473.5 2359.09   478.5 2358.76   483.5  2360.2   488.2 2361.54
   507.7 2373.12   536.8 2389.55   556.3 2400.33   585.5 2415.48   604.9 2426.63
   685.6  2479.2     736  2512.6   756.1 2524.26   766.2 2529.33   776.3 2533.46
   786.4 2535.77   806.6 2537.58   826.7 2536.79     867 2531.34   877.1 2530.54
#Mann= 3 , 0 , 0
       0     .06       0   473.5    .045       0   483.5     .06       0
Bank Sta=473.5,483.5
XS Rating Curve= 0 ,0
Exp/Cntr=0.3,0.1

Type RM Length L Ch R = 1 ,2235    ,229.6,232,234.4
XS GIS Cut Line= 4
      1867477.94      137359.414     1867260.155      137434.991
      1866977.59      137627.459     1866775.919      137857.211
#Sta/Elev= 30
      10 2555.97   120.3 2492.32   130.3 2486.94   150.3 2477.63   190.4 2459.58
   341.1 2392.42   381.4 2374.98   411.5 2362.34   431.6 2353.38   436.7 2352.13
   441.7  2350.9   446.7 2351.52   451.7 2352.15   461.8 2357.07   481.9  2371.2
     502 2383.42   512.1 2388.93   562.4 2414.69     602 2435.43   631.6 2452.18
   641.4 2458.07   661.2  2470.6   710.5 2502.97   730.2 2516.41   749.9 2530.36
   769.6 2543.72   779.5  2550.8   838.7 2596.68   868.3  2620.4   878.1 2627.96
#Mann= 3 , 0 , 0
       0     .06       0   436.7    .045       0   446.7     .06       0
Bank Sta=436.7,446.7
XS Rating Curve= 0 ,0
Exp/Cntr=0.3,0.1

Type RM Length L Ch R = 1 ,2003    ,213.4,212.1,210.8
XS GIS Cut Line= 4
     1867359.315      137161.332     1867092.068      137292.961
     1866816.843      137436.557     1866637.349      137628.017
#Sta/Elev= 30
     9.9 2557.69    49.7 2529.33   109.2 2486.08   119.2 2478.98   129.1  2472.6
     139 2467.71   208.5 2438.24   428.1 2347.11   438.1 2343.08   448.1    2340
   453.1 2339.34   458.1 2338.67   463.1  2339.3   468.1 2339.93   488.2 2348.92
   518.2 2360.78   528.2 2364.92   538.2 2369.41   558.3 2378.88   568.3 2383.88
   578.3 2389.35   608.3 2406.92   668.9 2442.86   699.2 2460.06   759.7 2495.63
   769.8 2501.86   810.2 2527.89   830.4 2540.62   860.7 2561.05   870.8 2567.34
#Mann= 3 , 0 , 0
       0     .06       0   453.1    .045       0   463.1     .06       0
Bank Sta=453.1,463.1
XS Rating Curve= 0 ,0
Exp/Cntr=0.3,0.1

Type RM Length L Ch R = 1 ,1790.9  ,269.7,266.1,262.5
XS GIS Cut Line= 4
     1867263.505      136999.468     1866992.907      137096.475
      1866768.26      137234.326     1866440.304      137350.578
#Sta/Elev= 30
     9.9 2545.36    29.7 2535.05    49.6 2522.29    59.5 2514.76    79.3  2497.5
     109 2466.41   118.9 2459.52   198.2 2422.49   257.7 2396.16   404.6 2336.56
   424.1 2329.34   438.6 2325.22   443.6  2324.2   448.6 2324.49   453.4 2324.77
   463.2 2327.83   472.9 2331.69     512 2344.82   580.9 2374.94   610.7 2390.22
   640.5 2407.91   670.3 2427.36   700.2 2449.16     720 2465.62   739.9  2480.8
   769.7 2501.44   799.6 2519.66   859.2 2554.02   879.1 2564.69     899 2573.61
#Mann= 3 , 0 , 0
       0     .06       0   438.6    .045       0   448.6     .06       0
Bank Sta=438.6,448.6
XS Rating Curve= 0 ,0
Exp/Cntr=0.3,0.1

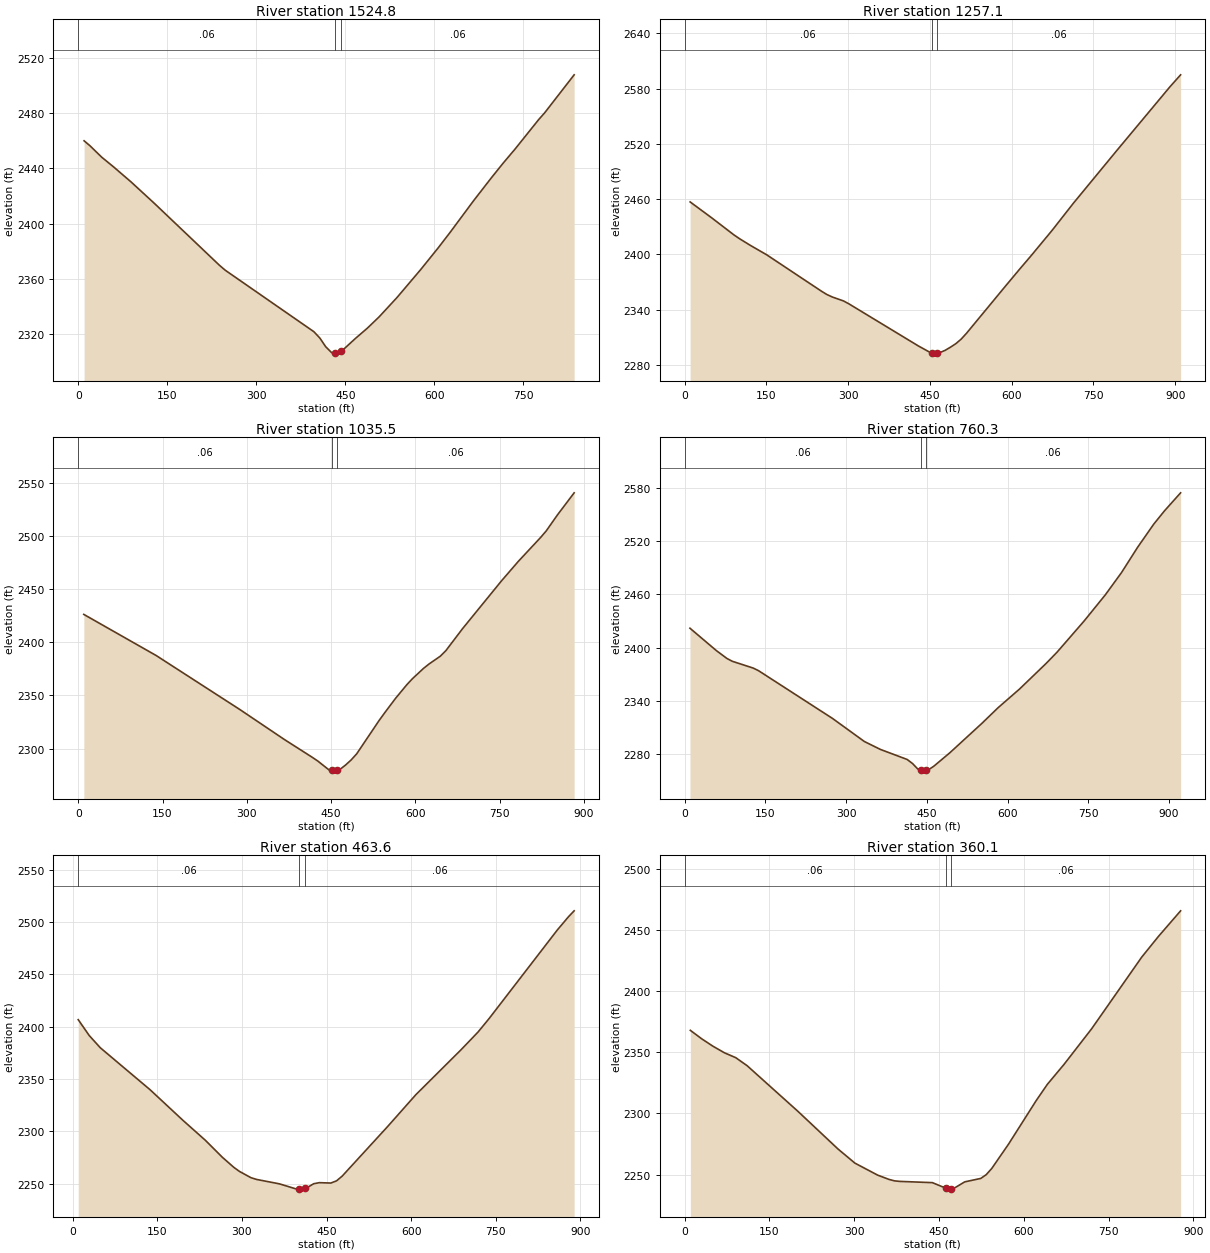
Type RM Length L Ch R = 1 ,1524.8  ,265.1,267.7,270.2
XS GIS Cut Line= 4
     1867080.101      136726.557     1866824.821      136858.186
      1866601.45      137057.624     1866413.978      137221.164
#Sta/Elev= 30
     9.9 2459.97    19.8 2456.37    39.6 2448.07    59.4 2441.11    89.1 2430.12
   128.8 2414.39   237.7  2369.8   247.6 2366.15     397 2321.56     407 2316.98
     417 2310.62     427 2306.34   431.9 2306.19   436.9 2306.03   441.9 2307.39
   446.9 2308.75   466.9 2316.65   486.9 2324.06   506.8 2332.28   536.8 2346.25
   576.7 2366.49   606.6 2382.46   626.5  2393.6   666.3 2416.69   696.1 2433.21
     716 2443.86   735.9 2453.99   775.7 2475.37   785.7 2480.23   835.4 2507.79
#Mann= 3 , 0 , 0
       0     .06       0   431.9    .045       0   441.9     .06       0
Bank Sta=431.9,441.9
XS Rating Curve= 0 ,0
Exp/Cntr=0.3,0.1

Type RM Length L Ch R = 1 ,1257.1  ,224.5,221.6,218.8
XS GIS Cut Line= 4
      1866942.36      136488.203     1866671.723      136661.803
     1866461.923      136805.455     1866234.724      137050.524
#Sta/Elev= 30
      10 2457.07    50.2 2439.51    90.4 2421.26   100.5 2417.19   120.6 2409.86
   150.7 2399.58   251.2 2360.05   261.2 2356.44   271.3 2353.74   291.4 2349.57
   301.4 2346.39   429.1 2300.59   448.7 2294.21   453.4 2293.57   458.4  2292.9
   463.4 2293.19   468.2 2293.48     478 2295.96   487.8 2299.38   497.6 2303.19
   507.3 2308.08   517.1 2314.43   585.6  2363.5   615.1 2384.41   634.8 2398.05
   674.1 2426.11   713.4 2455.76     792 2512.21   890.3 2581.98     910 2595.05
#Mann= 3 , 0 , 0
       0     .06       0   453.4    .045       0   463.4     .06       0
Bank Sta=453.4,463.4
XS Rating Curve= 0 ,0
Exp/Cntr=0.3,0.1

Type RM Length L Ch R = 1 ,1035.5  ,275.9,275.2,274.6
XS GIS Cut Line= 4
     1866788.922      136295.771     1866517.686      136479.254
     1866342.181      136638.805     1866158.698      136898.074
#Sta/Elev= 30
     9.9 2426.25   138.9 2387.52   287.8 2336.73     367 2308.56   416.4  2291.9
   426.3 2288.37   446.1 2280.09   450.9 2279.51   455.9 2278.91   460.9 2279.76
   465.8 2280.59   475.7 2284.67   485.6 2289.43   495.5 2295.22     535 2326.26
   544.9  2333.5   564.7 2347.41   584.5 2360.06   594.4 2365.69   614.3 2375.47
   624.2 2379.64   644.1  2386.9     654 2392.11   683.8 2412.85   753.2 2457.86
     783 2476.08   822.7 2498.58   832.7 2504.78   852.5 2519.68   882.3 2540.51
#Mann= 3 , 0 , 0
       0     .06       0   450.9    .045       0   460.9     .06       0
Bank Sta=450.9,460.9
XS Rating Curve= 0 ,0
Exp/Cntr=0.3,0.1

Type RM Length L Ch R = 1 ,760.3   ,302.8,296.6,290.4
XS GIS Cut Line= 4
     1866632.961      136121.303      1866349.44      136256.425
     1866178.562      136422.534     1865984.548      136736.529
#Sta/Elev= 30
     9.8 2421.87    58.9 2396.61    78.5 2387.75    88.3  2384.6   127.6 2376.85
   137.4 2373.91   274.8 2320.06   333.9 2294.08   363.7 2285.16   413.4 2273.83
   423.3 2269.29   433.2 2263.03   438.2 2261.86   443.2 2260.68   448.2 2261.45
   453.1  2262.2     463 2266.27   492.8 2281.43   552.4 2314.64   582.3 2332.17
   622.2 2353.27   672.1 2382.44     692 2394.91   741.9 2429.78   781.8 2459.66
   811.8 2484.72   841.7 2513.23   871.6 2539.27   891.6 2554.29   921.5 2574.56
#Mann= 3 , 0 , 0
       0     .06       0   438.2    .045       0   448.2     .06       0
Bank Sta=438.2,448.2
XS Rating Curve= 0 ,0
Exp/Cntr=0.3,0.1

Type RM Length L Ch R = 1 ,463.6   ,110.8,103.5,96.2
XS GIS Cut Line= 4
     1866306.202      135835.388     1866130.058       135991.11
     1865999.865      136231.074     1865900.306      136598.678
#Sta/Elev= 30
     9.8 2406.75    29.4 2391.52      49 2379.86   137.1 2339.81   195.9 2310.29
   235.1 2291.48   265.4 2275.15   285.7 2265.54   295.8 2261.63     316 2255.68
   326.1 2253.99   366.6 2249.76   396.9 2244.78     402 2244.78  407.03 2244.73
     412 2245.68   417.1 2246.61   427.2 2249.88   437.3 2250.91   457.6 2250.54
   467.7 2252.63   477.8 2257.18   558.2 2304.49   608.3 2334.97   688.5 2377.97
   718.6  2394.9   738.6 2408.05   858.9 2492.29   878.9 2505.09     889 2510.79
#Mann= 3 , 0 , 0
     9.8     .06       0     402    .045       0     412     .06       0
Bank Sta=402,412
XS Rating Curve= 0 ,0
Exp/Cntr=0.3,0.1

Type RM Length L Ch R = 1 ,360.1   ,70,75.3,80.5
XS GIS Cut Line= 4
     1866182.587      135713.522     1865969.533      136017.884
     1865945.184      136178.182     1865837.643      136504.864
#Sta/Elev= 30
      10 2368.03    30.1  2361.1    50.2 2354.98    70.3 2349.67    90.4 2345.65
   110.5  2339.1   200.8 2301.59   271.1 2271.03   301.2  2259.4   341.4 2249.58
   361.5 2246.07   371.5 2244.85   381.1 2244.43   438.3 2243.42   461.9 2238.92
   466.9 2238.11   471.9 2238.44   476.4 2238.74   495.5 2244.04   524.1 2246.88
   533.7    2250   543.5 2255.08     573 2274.85   622.1 2310.58   641.7 2323.79
   671.2 2340.11   720.4 2369.46   808.8 2427.94   838.3 2444.83   877.6  2465.8
#Mann= 3 , 0 , 0
       0     .06       0   461.9    .045       0   471.9     .06       0
Bank Sta=461.9,471.9
XS Rating Curve= 0 ,0
Exp/Cntr=0.3,0.1

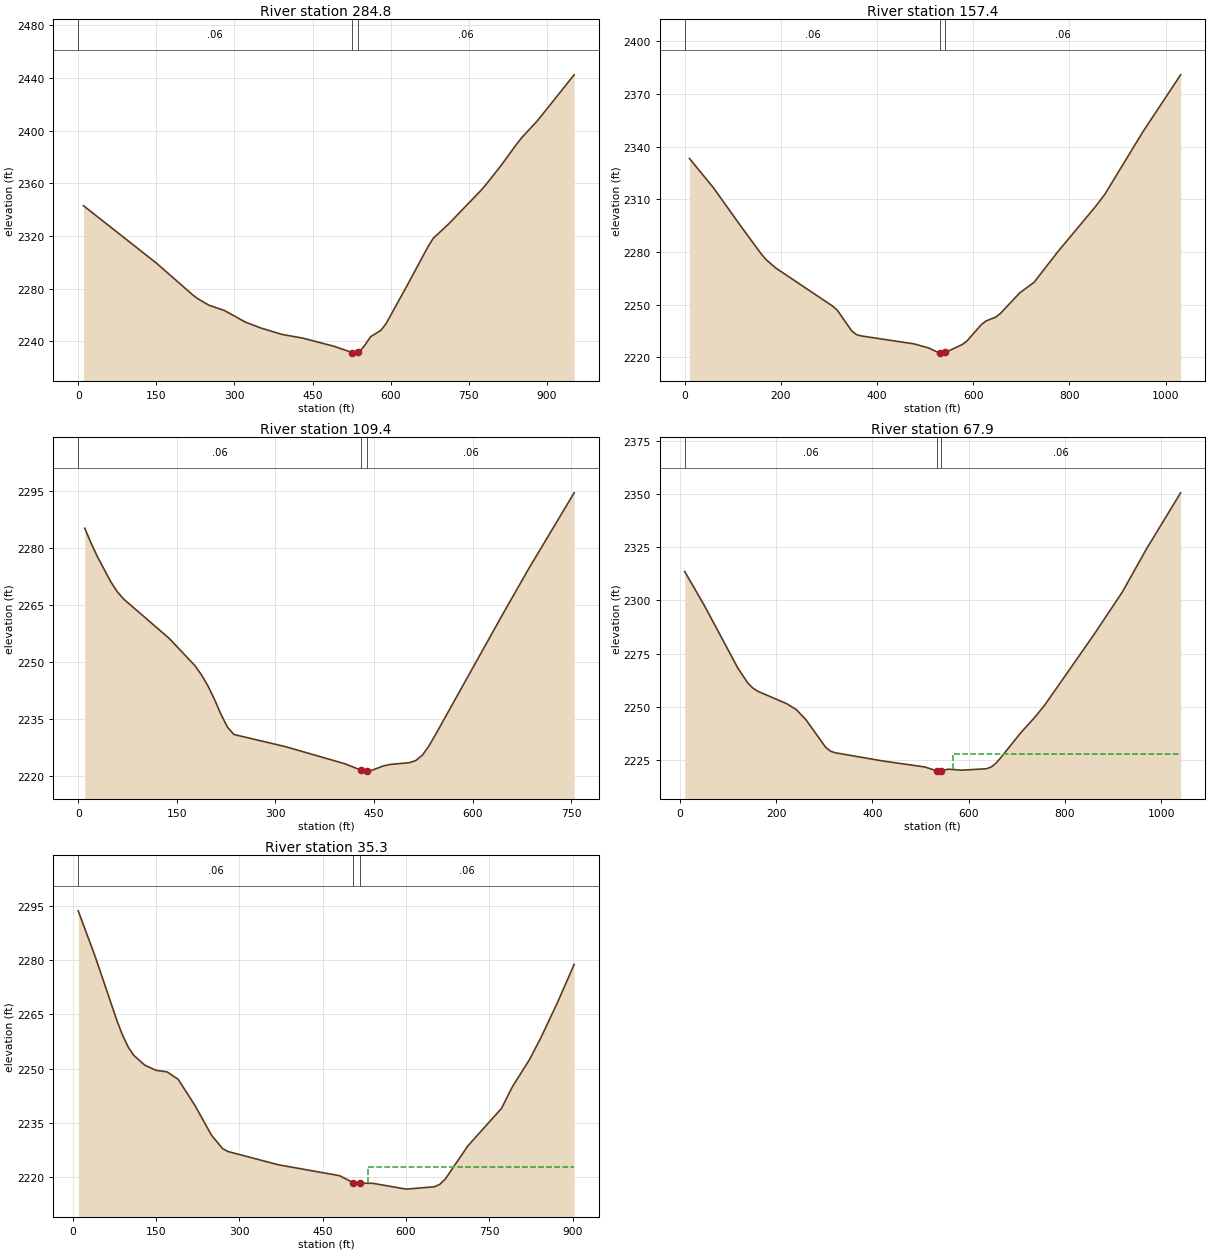
Type RM Length L Ch R = 1 ,284.8   ,124.4,127.4,130.4
XS GIS Cut Line= 4
     1866145.375      135654.139     1865989.654      135850.705
     1865839.039       136200.44     1865762.454      136511.882
#Sta/Elev= 30
      10 2343.07   150.5 2299.32   220.7    2275   230.7 2272.13   250.8 2267.48
   280.8 2263.42   320.9 2254.63     351 2250.08   391.1 2245.27   431.1 2242.45
   491.3 2236.21   526.4 2231.47   531.4 2231.04   536.4 2231.83   541.4 2232.63
   551.4 2237.61   561.4 2243.51   581.5 2248.43   591.5 2253.66   631.6 2282.44
   671.7 2311.92   681.7 2318.22   711.7 2329.32   771.9 2354.04   781.9 2358.54
     812 2373.55     842  2389.9   852.1 2394.89   882.1 2407.74   952.3 2442.45
#Mann= 3 , 0 , 0
       0     .06       0   526.4    .045       0   536.4     .06       0
Bank Sta=526.4,536.4
XS Rating Curve= 0 ,0
Exp/Cntr=0.3,0.1

Type RM Length L Ch R = 1 ,157.4   ,48.5,48,47.5
XS GIS Cut Line= 4
     1866132.611      135633.717     1865839.039      135929.842
     1865675.659      136192.781     1865629.708      136494.013
#Sta/Elev= 30
     9.9  2333.3    59.6 2316.71   119.1 2293.87   158.9 2279.07   168.8 2275.85
   188.6 2271.09   307.8 2249.24   317.7 2246.82   347.5 2235.07   357.4 2233.01
   367.3 2232.27   476.9 2227.75   506.9 2225.46   526.8 2222.91   531.8  2222.7
   536.8 2222.48   541.8 2222.85   576.8 2227.32   586.7 2229.28   616.7 2238.68
   626.7  2240.8   646.7 2242.97   656.6 2245.07   696.6 2256.77   726.5 2262.76
   775.7 2280.13   854.3 2305.92     874 2313.02   952.6 2348.38  1031.3 2380.92
#Mann= 3 , 0 , 0
       0     .06       0   531.8    .045       0   541.8     .06       0
Bank Sta=531.8,541.8
XS Rating Curve= 0 ,0
Exp/Cntr=0.3,0.1

Type RM Length L Ch R = 1 ,109.4   ,39,41.5,44.1
XS GIS Cut Line= 4
     1866042.063      135698.207     1865771.898      135943.812
     1865701.726      136063.106     1865636.816      136305.201
#Sta/Elev= 30
     9.9 2285.07    19.7 2281.12    29.6 2277.47    49.3 2271.06    59.2 2268.43
    69.1 2266.45   138.2 2256.13   177.6 2248.92   187.5 2246.49   197.4 2243.58
   207.2 2240.08   217.1 2236.14     227 2232.75   236.8 2230.83   315.8  2227.6
   404.7 2223.17   429.3 2221.51   434.3 2221.19   439.3 2221.23   444.2 2221.26
     464 2222.55   473.9 2222.94   503.5 2223.41   513.5 2223.98   523.6 2225.43
   533.6 2227.87   543.6 2230.86   643.9 2261.95     684 2274.11   754.2 2294.39
#Mann= 3 , 0 , 0
       0     .06       0   429.3    .045       0   439.3     .06       0
Bank Sta=429.3,439.3
XS Rating Curve= 0 ,0
Exp/Cntr=0.3,0.1

Type RM Length L Ch R = 1 ,67.9    ,32.4,32.6,32.8
XS GIS Cut Line= 4
     1866096.872      135628.611     1865768.047      135895.768
     1865668.394      136024.511     1865586.311      136471.037
#Sta/Elev= 30
    10.1  2313.6    50.4 2297.86     121 2268.04   141.2 2261.26   151.3 2258.92
   161.4 2257.39   221.9 2251.52   242.1 2248.71   262.3  2243.9   302.6 2231.14
   312.7 2229.22   322.8 2228.46   423.7 2224.51   509.9 2221.74   533.6 2219.95
   538.6 2219.82   543.6 2220.11   557.7 2220.73   586.5 2220.28   636.9 2220.93
     647 2221.76   657.1  2223.6   667.2 2226.24   707.5 2237.61   737.8 2245.19
     758 2250.79   858.9 2283.45   919.4 2303.94   969.9 2324.33  1040.5 2350.54
#Mann= 3 , 0 , 0
    10.1     .06       0   533.6    .045       0   543.6     .06       0
#XS Ineff= 2 , 0
                          566.86         2227.72
Permanent Ineff=
       F       F
Bank Sta=533.6,543.6
XS Rating Curve= 0 ,0
Exp/Cntr=0.3,0.1

Type RM Length L Ch R = 1 ,35.3    ,38.5,35.3,32
XS GIS Cut Line= 4
     1866058.508      135639.498     1865733.691      135889.357
     1865615.173       136038.78     1865554.352      136334.665
#Sta/Elev= 30
      10 2293.55      40 2281.18      80 2263.14      90 2259.19     100 2255.96
   109.9  2253.7   129.9 2250.97   149.9 2249.56   169.9 2249.13   189.9 2247.07
   219.9 2239.92   249.9 2231.66   269.9 2227.94   279.9 2227.14   369.8 2223.51
   480.1  2220.5  504.87 2218.58  516.64 2218.43   540.3 2218.38   600.5 2216.78
   650.9 2217.43   660.9 2218.11     671 2219.62   711.3 2228.71   771.7 2239.02
   791.8 2245.12     822 2252.45   842.2 2258.39   872.4 2268.19   902.6 2278.76
#Mann= 3 , 0 , 0
      10     .06       0  504.87    .045       0  516.64     .06       0
#XS Ineff= 2 , 0
                          530.89         2222.98
Permanent Ineff=
       F       F
Bank Sta=504.87,516.64
XS Rating Curve= 0 ,0
Exp/Cntr=0.3,0.1

Chan Stop Cuts=-1
Use User Specified Reach Order=0